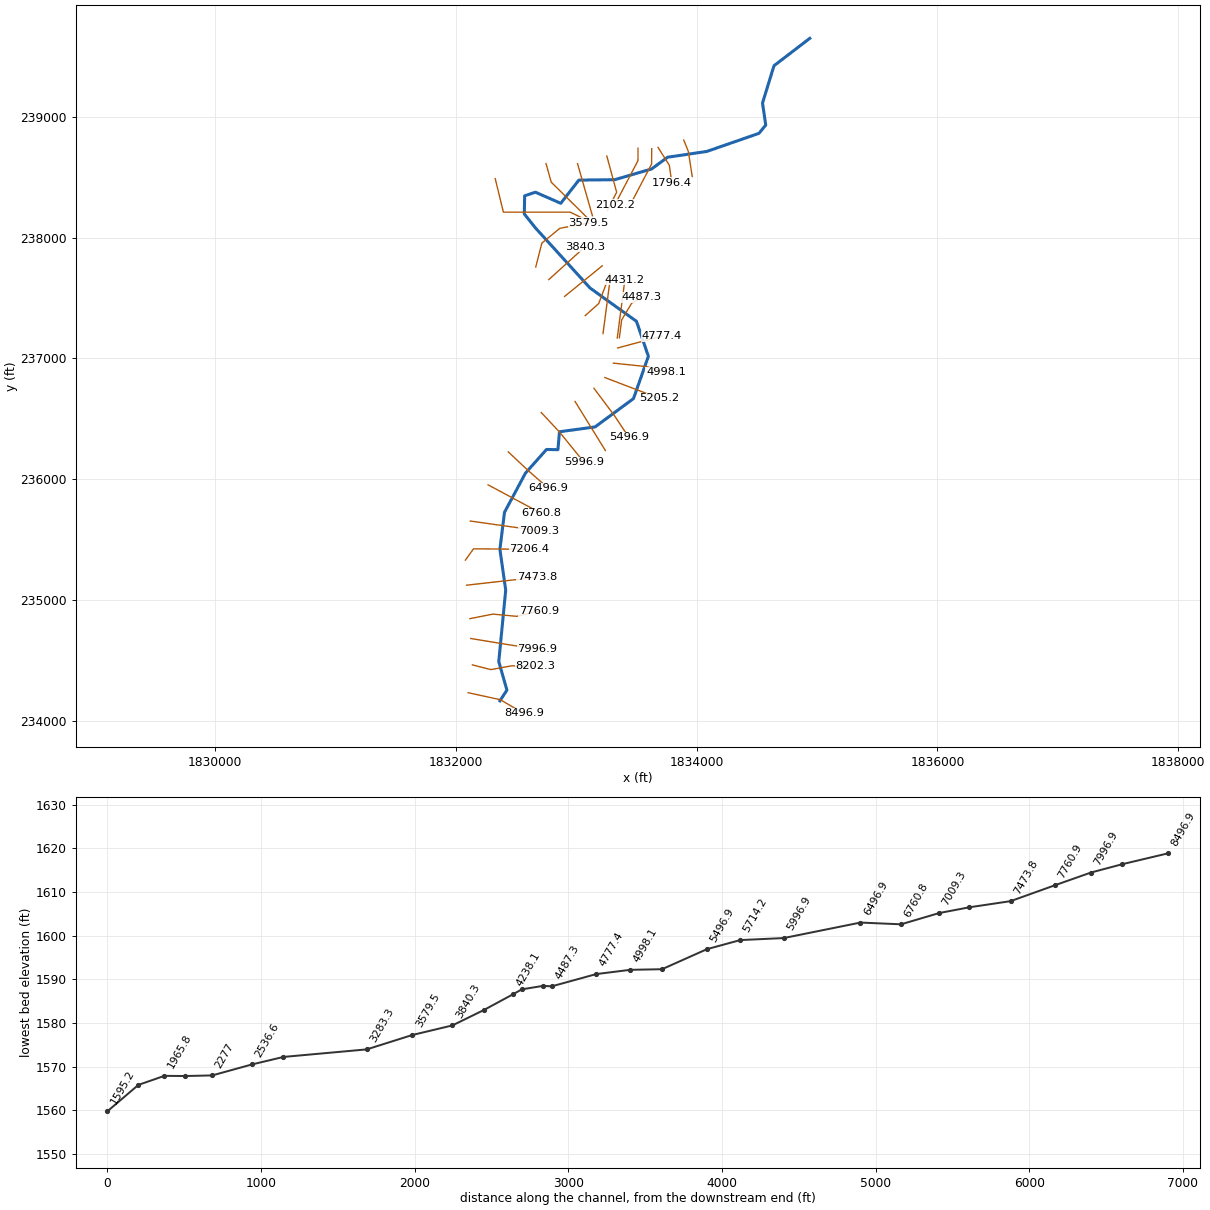
--- BONICARN.prj (project) ---

Proj Title=BONICARN
Current Plan=p01
Default Exp/Contr=0,0
English Units
Geom File=g01
Flow File=f01
Plan File=p01
BEGIN DESCRIPTION:
END DESCRIPTION:
DSS Export Rating Curves= 0
DSS Export Rating Curve Sorted= 0
DSS Export Volume Flow Curves= 0
DXF OffsetX= 0
DXF OffsetY= 0
DXF ScaleX= 0
DXF ScaleY= 0

--- BONICARN.p01 (plan) ---

Plan Title=Floodplain
Program Version=4.00
Geom File=g01
Flow File=f01
K Sum by GR=0
Std Step Tol=0.01
Critical Tol=0.01
Num of Std Step Trials=20
Max Error Tol=0.3
Flow Tol Ratio=0.001
Split Flow NTrial=30
Split Flow Tol=0.02
Split Flow Ratio=0.02
Log Output Level=0
Friction Slope Method=1
Unsteady Friction Slope Method=2
Unsteady Bridges Friction Slope Method=1
Global Log Level=0
CheckData=False
Run HTab=0
Run UNet=0
Run PostProcess=0
UNET Theta=0
UNET Theta Warmup=0
UNET ZTol=0
UNET ZSATol=0
UNET MxIter=0
UNET MaxInSteps=0
UNET DtIC=0
UNET DtMin=0
UNET MaxCRTS=0
UNET WFStab=0
UNET SFStab=0
UNET WFX=0
UNET SFX=0
UNET DSS MLevel=0
UNET DZMax Abort=0
UNET Convert EG Bridges=0
UNET Use Existing IB Tables=0
UNET Froude Limit=0
UNET Froude Power=0
Write IC File=0
Echo Input=False
Echo Output=False
Write Detailed=0

--- BONICARN.f01 (steady flow) ---

Flow Title=NFF Regression Equation
Program Version=4.00
Number of Profiles=1
Profile Names=P100yr
River Rch & RM=BONICARN,Main      ,8496.9
666.8941
River Rch & RM=BONICARN,Main      ,7009.3
697.5065
River Rch & RM=BONICARN,Main      ,6760.8
879.4497
River Rch & RM=BONICARN,Main      ,5496.9
897.4891
River Rch & RM=BONICARN,Main      ,462.3
994.2339
River Rch & RM=BONICARN,Main      ,244.3
1000.346
Boundary for River Rch & Prof#=BONICARN,Main      ,1
Up Type=0
Dn Type=3
Dn Slope=0.050294

--- BONICARN.g01 (geometry) ---

Geom Title=USGS 10m DEM
Program Version=4.10

River Reach=BONICARN        ,Main
Reach XY= 30
        1832365.      234164.709     1832423.414      234253.634
      1832355.69      234489.899      1832413.27       235081.62
     1832365.084      235419.812     1832403.165        235725.9
     1832576.982      236049.884     1832752.167      236246.499
     1832847.089      236244.559     1832860.028      236392.971
     1833155.863      236433.289     1833474.729      236667.513
     1833598.441      237018.139     1833499.806      237307.329
      1833113.09      237584.064     1832661.139      238080.231
     1832567.772      238196.631     1832570.571      238346.578
     1832659.862      238377.121     1832870.683       238285.03
     1833020.926      238477.159      1833319.48      238480.448
      1833625.68      238569.676     1833758.184      238666.594
     1834083.093      238714.282     1834516.911      238864.216
     1834573.232      238932.714     1834546.594      239115.375
     1834641.932      239424.246     1834939.316      239651.174

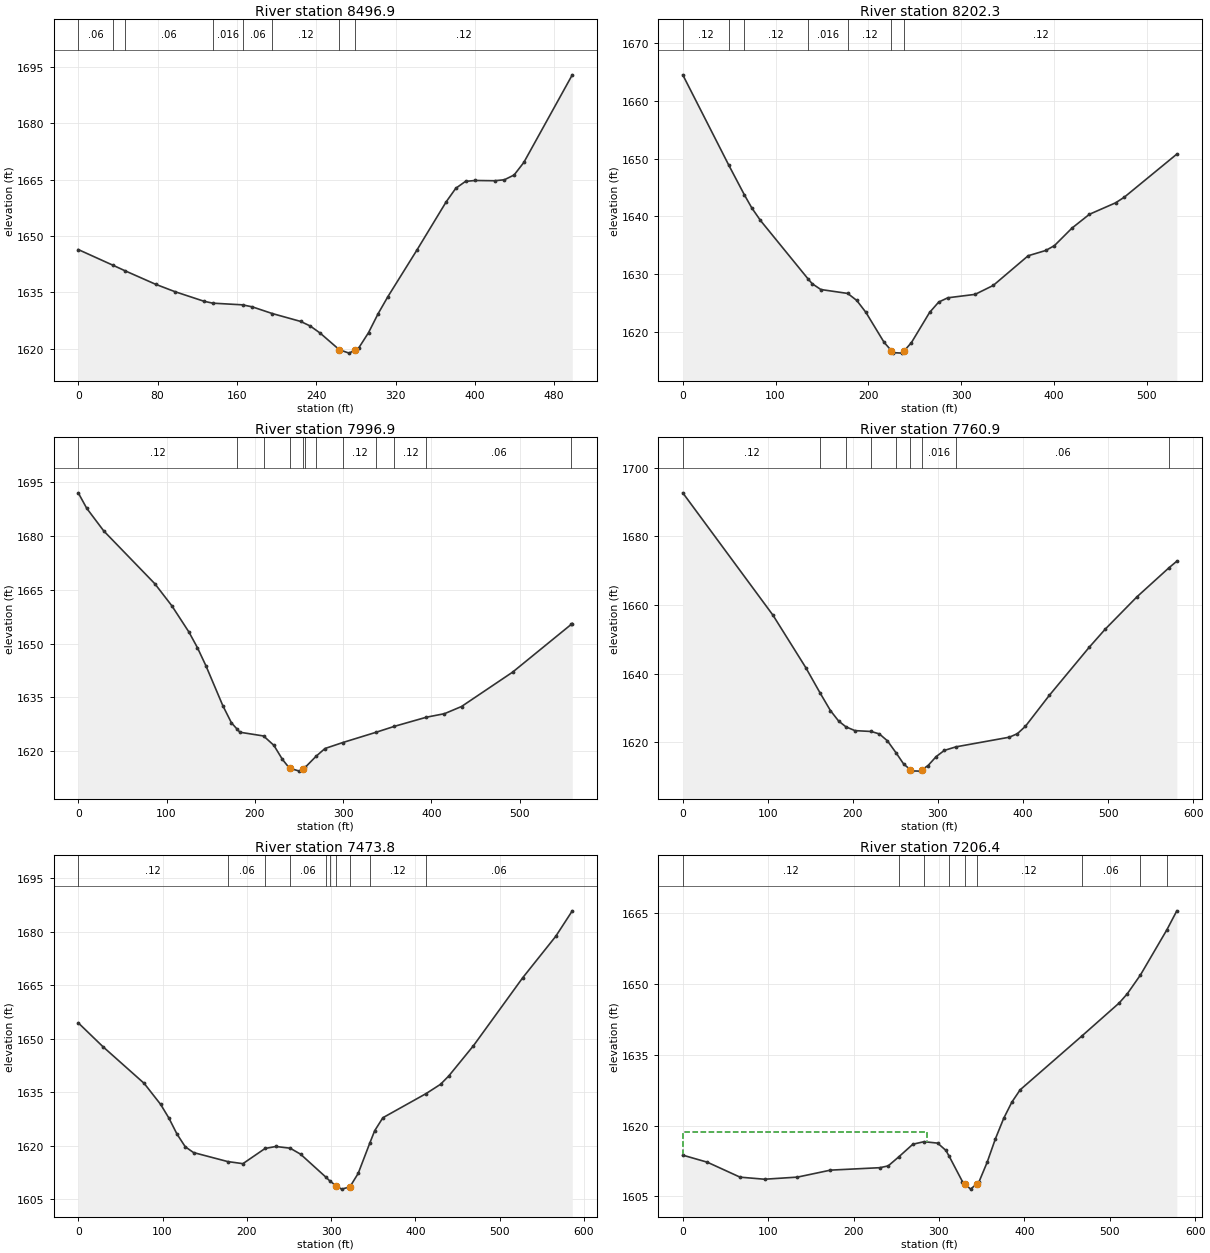
Type RM Length L Ch R = 1 ,8496.9  ,285.6,294.7,310.8
XS GIS Cut Line= 3
     1832101.454      234232.055     1832368.406      234174.112
      1832562.99      234060.836
#Sta/Elev= 30
       0  1646.4   34.851642.242    47.21640.749      78 1637.16    97.6 1635.18
   126.8 1632.64  135.581632.129  165.691631.681   175.6 1631.14  195.811629.357
   224.4 1627.26   234.1 1626.03   243.9 1624.18   263.4 1619.72   273.2 1618.83
  279.04 1619.66     283 1620.25   292.8 1624.29   302.5 1629.35   312.3 1633.86
   341.7 1646.31   371.1  1659.1   380.8 1662.71   390.6 1664.54   400.4 1664.78
     420 1664.71   429.8 1664.97   439.6 1666.24   449.4 1669.58   498.3  1692.9
#Mann= 8 ,-1 , 0
       0     .06       0   34.85     .12       0    47.2     .06       0
  135.58    .016       0  165.69     .06       0  195.81     .12       0
   263.4    .045       0  279.04     .12       0
Bank Sta=263.4,279.04
XS Rating Curve= 0 ,0
Exp/Cntr=0.3,0.1

Type RM Length L Ch R = 1 ,8202.3  ,213,205.3,197.7
XS GIS Cut Line= 4
     1832136.457      234462.338     1832289.744      234423.444
     1832463.355      234454.694     1832661.211      234452.056
#Sta/Elev= 30
       0  1664.5   49.511648.901    66.51643.714    74.4 1641.48    83.7 1639.32
  134.921629.227   139.5 1628.37   148.8 1627.37  177.761626.693   187.5 1625.48
   197.3 1623.43   216.9 1618.25   224.9 1616.78   226.8 1616.45   236.6 1616.37
  238.91 1616.82   246.4 1618.19     266 1623.41   275.8  1625.2   285.6 1625.94
     315 1626.53   334.6 1628.08   372.2 1633.21   391.1 1634.12   400.5 1634.96
   419.4 1637.99   438.2 1640.38   466.5 1642.37   475.9 1643.35   532.4 1650.79
#Mann= 7 ,-1 , 0
       0     .12       0   49.51     .06       0    66.5     .12       0
  134.92    .016       0  177.76     .12       0   224.9    .045       0
  238.91     .12       0
Bank Sta=224.9,238.91
XS Rating Curve= 0 ,0
Exp/Cntr=0.3,0.1

Type RM Length L Ch R = 1 ,7996.9  ,234.3,236,237.4
XS GIS Cut Line= 3
     1832122.809       234680.99     1832370.065        234640.4
     1832675.211      234591.385
#Sta/Elev= 30
       0 1692.07     9.6 1687.76    28.9 1681.44    86.7 1666.73     106 1660.57
   125.3 1653.27   134.9 1648.93   144.6 1643.85   163.8 1632.69   173.5 1627.93
  180.031626.141   183.1  1625.3  209.881624.255   221.6 1621.64   231.3 1617.71
  239.29 1615.26   250.6 1614.45  255.07 1615.16  257.081615.512  269.581618.641
   279.5 1620.76  299.421622.406  337.691625.315  358.121626.943  394.451629.494
   414.8 1630.47   434.1 1632.47     492 1642.06  558.441655.386   559.6 1655.62
#Mann= 12 ,-1 , 0
       0     .12       0  180.03    .016       0  209.88     .12       0
  239.29    .045       0  255.07     .12       0  257.08     .06       0
  269.58    .016       0  299.42     .12       0  337.69     .06       0
  358.12     .12       0  394.45     .06       0  558.44     .12       0
Bank Sta=239.29,255.07
XS Rating Curve= 0 ,0
Exp/Cntr=0.3,0.1

Type RM Length L Ch R = 1 ,7760.9  ,282.2,287.2,291.4
XS GIS Cut Line= 4
     1832116.133      234845.319     1832305.307      234882.837
     1832505.022      234864.417     1832687.314      234907.819
#Sta/Elev= 30
       0 1692.73   106.1    1657   144.6 1641.73  161.611634.255   173.6 1629.19
   183.2 1626.15  191.821624.444   202.4 1623.34  221.46 1623.09   231.1 1622.38
   240.6 1620.36  251.081616.748   259.7 1613.59  267.31 1611.99   269.3 1611.59
   278.8 1611.52   281.4 1611.96   288.4 1613.16   297.9 1615.76   307.5 1617.57
  321.171618.604   383.9 1621.42   393.4 1622.45   402.8  1624.6   430.9 1633.63
   477.8 1647.66   496.5 1652.91     534  1662.4  571.821670.917   580.8 1672.78
#Mann= 9 ,-1 , 0
       0     .12       0  161.61     .06       0  191.82    .016       0
  221.46     .06       0  251.08     .12       0  267.31    .045       0
   281.4    .016       0  321.17     .06       0  571.82     .12       0
Bank Sta=267.31,281.4
XS Rating Curve= 0 ,0
Exp/Cntr=0.3,0.1

Type RM Length L Ch R = 1 ,7473.8  ,270,267.3,264.6
XS GIS Cut Line= 2
      1832088.36      235122.425     1832670.957      235187.819
#Sta/Elev= 30
       0 1654.47    29.3 1647.79    78.2 1637.52    97.7 1631.65   107.5 1627.83
   117.2 1623.31     127 1619.76   136.8 1618.14   177.31615.621   195.4 1615.03
   221.71619.282   234.5 1619.84  251.481619.361   263.8 1617.69  293.861611.258
   298.51610.207  306.46 1608.74   312.7  1607.9   322.4 1608.54   332.2  1612.3
  346.041620.828   351.8 1624.26   361.5 1627.89  412.721634.644   429.9 1637.25
   439.7 1639.59     469 1648.06   527.6 1667.14   566.7 1678.71   586.3 1685.83
#Mann= 10 ,-1 , 0
       0     .12       0   177.3     .06       0   221.7    .016       0
  251.48     .06       0  293.86     .12       0   298.5     .06       0
  306.46    .045       0   322.4     .06       0  346.04     .12       0
  412.72     .06       0
Bank Sta=306.46,322.4
XS Rating Curve= 0 ,0
Exp/Cntr=0.3,0.1

Type RM Length L Ch R = 1 ,7206.4  ,200.1,197.1,194.1
XS GIS Cut Line= 3
       1832078.6      235330.006     1832145.647      235423.444
     1832609.189      235419.972
#Sta/Elev= 30
       0 1613.71    28.8 1612.21    67.1 1609.04    95.8  1608.6   134.3 1609.05
     173 1610.53   230.9 1611.05   240.6 1611.43  253.061613.361   269.5 1616.03
   282.61616.565   298.5 1616.26   308.2 1614.71  312.141613.425   327.5 1608.11
  330.44 1607.59   337.1  1606.5  344.29 1607.61   346.8 1607.99   356.4 1612.16
   366.1 1617.16   375.8  1621.5   385.4 1624.96   395.1 1627.57     4671638.926
     511 1645.98   520.6 1647.95  535.96 1651.93  566.991661.538   578.6 1665.55
#Mann= 9 ,-1 , 0
       0     .12       0  253.06     .06       0   282.6    .016       0
  312.14     .12       0  330.44    .045       0  344.29     .12       0
     467     .06       0  535.96     .12       0  566.99     .06       0
#XS Ineff= 2 , 0
          286.07 1618.68
Permanent Ineff=
       F       F
Bank Sta=330.44,344.29
XS Rating Curve= 0 ,0
Exp/Cntr=0.3,0.1

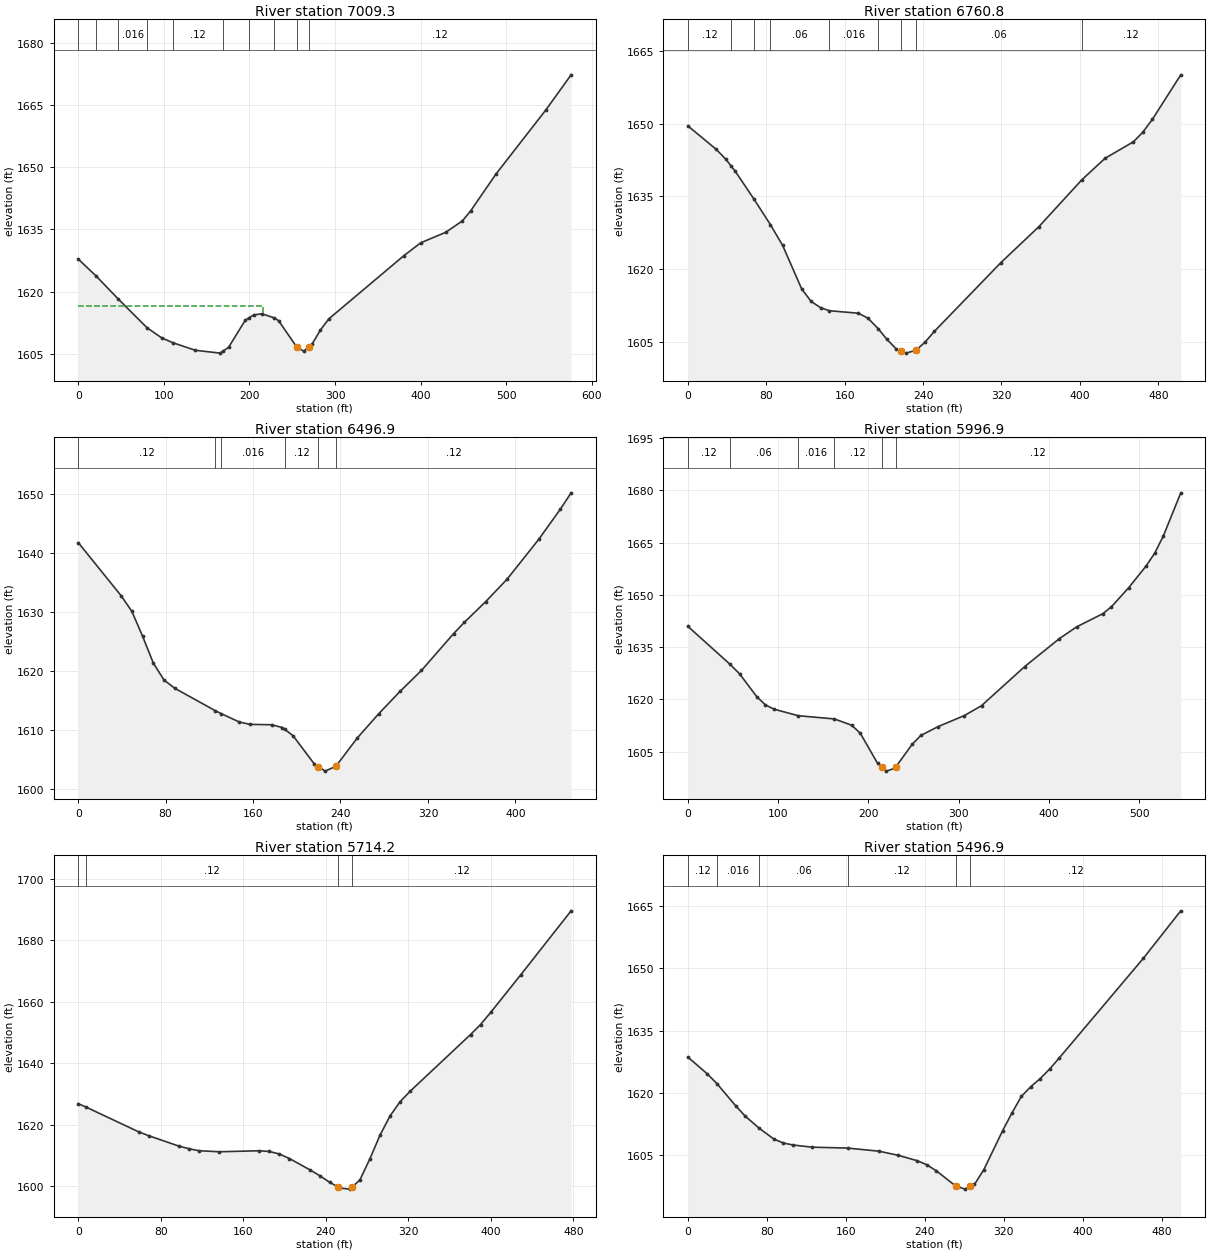
Type RM Length L Ch R = 1 ,7009.3  ,256.4,248.6,240.5
XS GIS Cut Line= 2
     1832119.066      235653.737     1832689.252      235573.499
#Sta/Elev= 30
       0 1627.86   20.931623.775   46.75 1618.23   80.451611.295    97.6 1608.85
  110.21 1607.72   136.6 1605.87   165.9 1605.18  169.741605.729   175.7 1606.58
   195.2 1613.12   199.51613.682     205  1614.4   214.7 1614.65  229.261613.663
   234.2 1612.97  255.03 1606.73   263.5 1605.64  269.78 1606.73   273.3 1607.39
     283 1610.77   292.8 1613.44   380.6  1628.7   400.1 1631.77   429.4 1634.31
   448.9 1637.07   458.7 1639.54     488 1648.34   546.5 1663.85   575.8 1672.26
#Mann= 10 ,-1 , 0
       0     .12       0   20.93     .06       0   46.75    .016       0
   80.45     .06       0  110.21     .12       0  169.74     .08       0
   199.5    .016       0  229.26     .12       0  255.03    .045       0
  269.78     .12       0
#XS Ineff= 2 , 0
           216.1 1616.49
Permanent Ineff=
       F       F
Bank Sta=255.03,269.78
XS Rating Curve= 0 ,0
Exp/Cntr=0.3,0.1

Type RM Length L Ch R = 1 ,6760.8  ,269.6,263.9,258.6
XS GIS Cut Line= 2
     1832267.193       235953.27     1832710.751      235716.196
#Sta/Elev= 30
       0 1649.54      29 1644.68    38.7 1642.66    44.11641.263    48.4 1640.15
   67.481634.407   84.161629.162    96.7 1624.85   116.1 1615.88   125.7 1613.29
   135.4 1611.99  144.461611.355   174.1 1610.84   183.8 1609.81  194.451607.598
   203.1 1605.44   212.8 1603.42   217.4 1603.03   222.4  1602.6   232.4 1603.16
   241.8 1604.81   251.5 1607.09   319.2 1621.26   357.9 1628.67  401.831638.373
   425.6 1642.83   454.6 1646.25   464.2 1648.23   473.9 1650.87   502.9 1660.08
#Mann= 9 ,-1 , 0
       0     .12       0    44.1     .06       0   67.48     .12       0
   84.16     .06       0  144.46    .016       0  194.45     .12       0
   217.4    .045       0   232.4     .06       0  401.83     .12       0
Bank Sta=217.4,232.4
XS Rating Curve= 0 ,0
Exp/Cntr=0.3,0.1

Type RM Length L Ch R = 1 ,6496.9  ,490.9,500,496
XS GIS Cut Line= 3
     1832434.852      236226.162     1832599.817      236071.636
     1832769.302      235923.719
#Sta/Elev= 30
       0 1641.83    39.3 1632.79    49.1 1630.14      59 1625.88    68.8 1621.33
    78.6 1618.46    88.4 1617.07  125.241613.285  131.051612.745   147.4 1611.35
   157.2 1610.94   176.9 1610.88   186.7 1610.41  188.891610.103   196.6 1609.02
   216.2 1604.17   219.8 1603.75     226    1603   235.8 1603.83   255.4 1608.64
   274.9 1612.73   294.5 1616.55   314.1  1620.1   343.4 1626.34   353.2 1628.25
   372.7 1631.76   392.3 1635.58   421.6 1642.42   441.2 1647.51     451 1650.27
#Mann= 6 ,-1 , 0
       0     .12       0  125.24     .06       0  131.05    .016       0
  188.89     .12       0   219.8    .045       0   235.8     .12       0
Bank Sta=219.8,235.8
XS Rating Curve= 0 ,0
Exp/Cntr=0.3,0.1

Type RM Length L Ch R = 1 ,5996.9  ,285.7,282.7,278.5
XS GIS Cut Line= 3
     1832708.802      236552.184      1832858.99       236391.83
     1833065.424      236139.157
#Sta/Elev= 30
       0 1640.99   46.531630.146    57.3 1627.37    76.4 1620.78      86 1618.43
    95.5 1617.22  122.331615.349  162.371614.421   181.5 1612.61     191 1610.33
   210.2 1601.66  214.98 1600.56   219.7 1599.45   229.3 1600.27  230.29 1600.63
   248.5 1607.15   258.1 1609.69   277.3 1612.24   306.1 1615.36   325.3 1618.23
   373.2 1629.46   411.6 1637.48   430.8 1640.86   459.6 1644.61   469.2  1646.6
   488.4  1652.1   507.6  1658.3   517.2    1662   526.8 1666.97     546 1679.29
#Mann= 6 ,-1 , 0
       0     .12       0   46.53     .06       0  122.33    .016       0
  162.37     .12       0  214.98    .045       0  230.29     .12       0
Bank Sta=214.98,230.29
XS Rating Curve= 0 ,0
Exp/Cntr=0.3,0.1

Type RM Length L Ch R = 1 ,5714.2  ,215.9,217.3,218.3
XS GIS Cut Line= 2
     1832989.397      236643.931     1833241.133      236237.681
#Sta/Elev= 30
       0 1626.82    7.16 1625.79    58.5 1617.67    68.3  1616.4    97.5 1613.02
   107.3 1612.15     117 1611.51   136.6 1611.16   175.6 1611.49   185.3 1611.25
   195.1 1610.43   204.8 1608.96   224.3 1605.34   234.1  1603.4   243.8 1601.22
  251.73 1599.74   253.6 1599.36   263.4 1598.99   265.7  1599.7   273.1 1601.97
   282.8 1608.85   292.6 1616.56   302.4 1622.86   312.1 1627.46   321.9  1630.9
   380.4 1649.35   390.1 1652.61   399.9 1656.55   429.2 1668.86   477.9 1689.65
#Mann= 4 ,-1 , 0
       0     .06       0    7.16     .12       0  251.73    .045       0
   265.7     .12       0
Bank Sta=251.73,265.7
XS Rating Curve= 0 ,0
Exp/Cntr=0.3,0.1

Type RM Length L Ch R = 1 ,5496.9  ,278.7,291.7,305.4
XS GIS Cut Line= 3
     1833146.293       236753.25     1833314.831      236528.639
     1833436.042       236346.95
#Sta/Elev= 30
       0 1628.63    19.4 1624.66   29.591622.217    48.4 1616.93    58.1 1614.44
    72.11611.563    87.2 1608.92    96.8 1607.98   106.5  1607.5   125.9 1606.98
  161.831606.764   193.7 1606.01     213 1605.03   232.4 1603.72   242.1 1602.74
   251.8 1601.27   271.1 1597.68   280.8  1596.9  286.24 1597.57   290.3 1598.03
   299.8  1601.6   318.8 1610.95   328.3 1615.23   337.8 1619.18   347.3 1621.52
   356.8 1623.45   366.3 1625.73   375.8 1628.32   461.2 1652.33   499.2 1663.77
#Mann= 6 ,-1 , 0
       0     .12       0   29.59    .016       0    72.1     .06       0
  161.83     .12       0   271.1    .045       0  286.24     .12       0
Bank Sta=271.1,286.24
XS Rating Curve= 0 ,0
Exp/Cntr=0.3,0.1

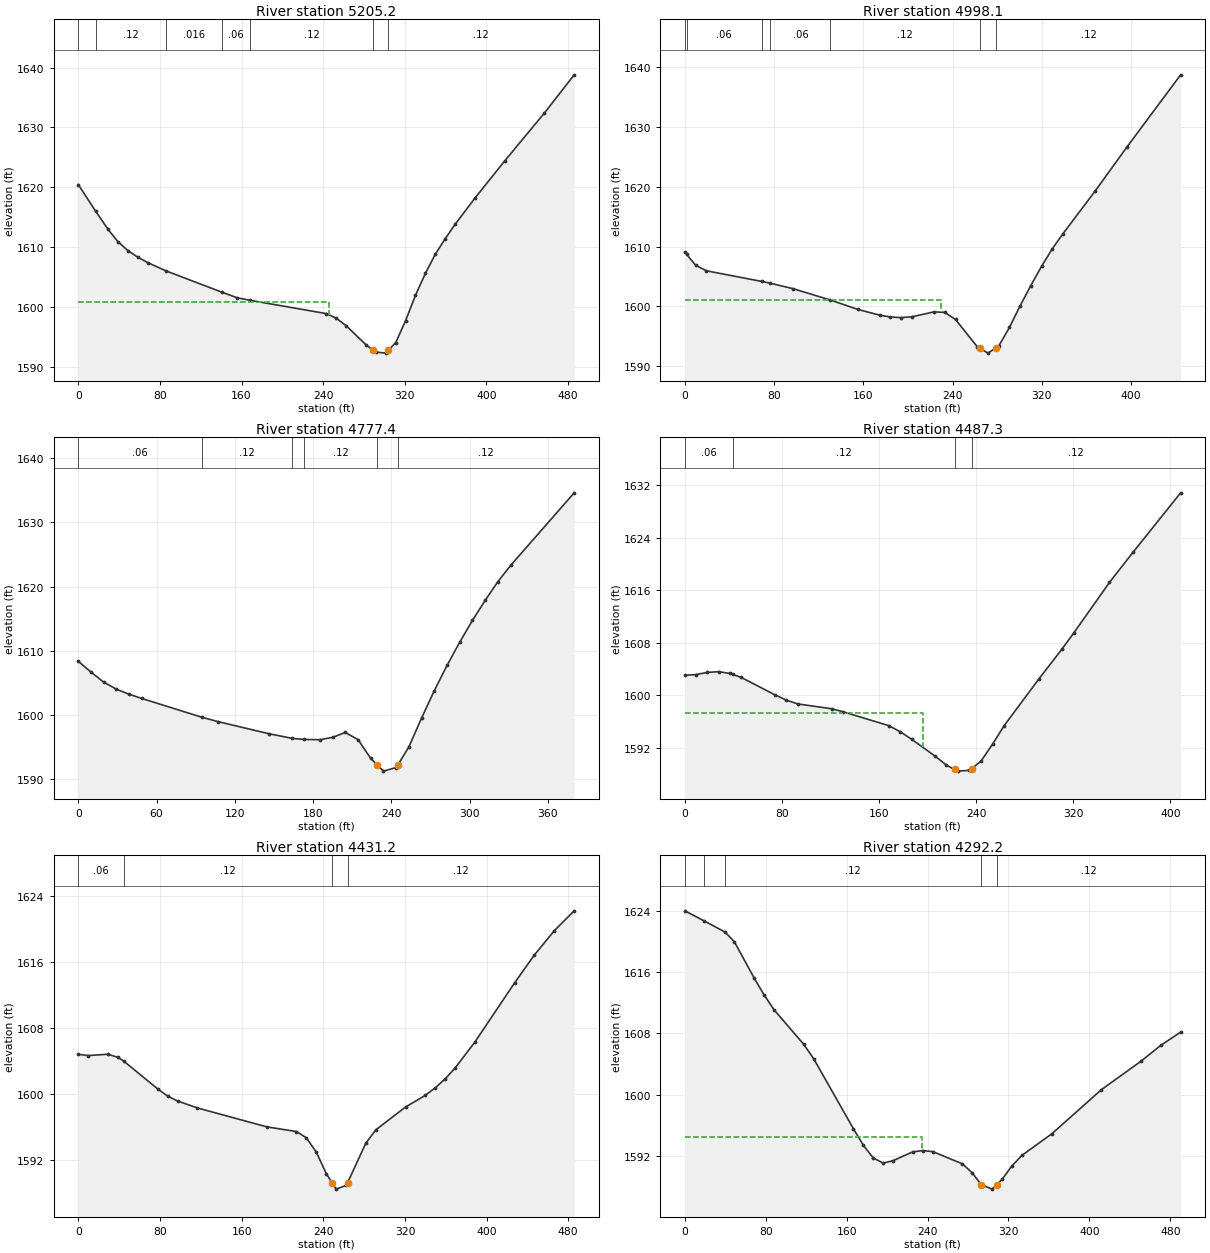
Type RM Length L Ch R = 1 ,5205.2  ,201.3,207.1,209.1
XS GIS Cut Line= 2
     1833236.558      236842.187     1833690.906      236669.169
#Sta/Elev= 30
       0 1620.45   16.971616.016    29.2 1612.97    38.9 1610.92    48.6 1609.44
    58.3 1608.34    68.1 1607.43   85.891606.053  141.121602.473   155.6 1601.57
  168.411601.137   243.1 1598.92   252.8 1598.16   262.5 1596.92     282 1593.73
  289.06 1592.79   291.7  1592.5   301.4 1592.32  303.94 1592.77   311.2 1594.06
   320.9 1597.74   330.6 1601.97   340.3 1605.63     350 1608.81   359.8 1611.44
   369.5 1613.83   388.9  1618.2   418.1 1624.41     457  1632.4   486.2 1638.78
#Mann= 7 ,-1 , 0
       0     .06       0   16.97     .12       0   85.89    .016       0
  141.12     .06       0  168.41     .12       0  289.06    .045       0
  303.94     .12       0
#XS Ineff= 2 , 0
          245.61  1600.9
Permanent Ineff=
       F       F
Bank Sta=289.06,303.94
XS Rating Curve= 0 ,0
Exp/Cntr=0.3,0.1

Type RM Length L Ch R = 1 ,4998.1  ,212.4,220.6,232.7
XS GIS Cut Line= 3
     1833308.109      236961.291     1833578.461      236933.085
     1833744.718      236886.567
#Sta/Elev= 30
       0 1609.07    1.661608.695     9.7 1606.88    19.4 1605.95    68.91604.175
   76.561603.875    97.1 1602.96  130.591601.059   155.3 1599.48   174.7 1598.53
   184.4 1598.22   194.2 1598.12   203.9 1598.27   223.3 1599.08     233    1599
   242.7 1597.81   262.1 1593.27   264.3 1593.02   271.8 1592.18   279.3  1593.1
   281.4 1593.36     291 1596.47   300.6  1600.1   310.2 1603.48   319.8 1606.69
   329.4 1609.62     339 1612.15   367.7 1619.25   396.5 1626.69   444.5 1638.73
#Mann= 7 ,-1 , 0
       0     .12       0    1.66     .06       0    68.9     .12       0
   76.56     .06       0  130.59     .12       0   264.3    .045       0
   279.3     .12       0
#XS Ineff= 2 , 0
          229.62 1601.06
Permanent Ineff=
       F       F
Bank Sta=264.3,279.3
XS Rating Curve= 0 ,0
Exp/Cntr=0.3,0.1

Type RM Length L Ch R = 1 ,4777.4  ,272.6,290.1,307.4
XS GIS Cut Line= 2
     1833342.832      237086.907     1833710.151      237185.036
#Sta/Elev= 30
       0 1608.34     9.8 1606.64    19.5 1605.09    29.2 1603.98      39  1603.2
    48.7 1602.54    94.61599.622   107.2 1598.93   146.2 1597.04  163.951596.321
  173.121596.154   185.2 1596.11     195 1596.48   204.7 1597.24   214.5 1596.12
   224.2  1593.2  229.21 1592.17     234 1591.21   243.7 1591.77  245.07 1592.19
   253.5 1595.01   263.2 1599.49     273 1603.78   282.7 1607.69   292.5 1611.35
   302.2 1614.72     312 1617.86   321.7 1620.76   331.5  1623.3   380.2 1634.62
#Mann= 6 ,-1 , 0
       0     .06       0    94.6     .12       0  163.95     .06       0
  173.12     .12       0  229.21    .045       0  245.07     .12       0
Bank Sta=229.21,245.07
XS Rating Curve= 0 ,0
Exp/Cntr=0.3,0.1

Type RM Length L Ch R = 1 ,4487.3  ,45,56.1,66.2
XS GIS Cut Line= 4
     1833357.453      237171.708      1833376.55      237319.278
     1833459.883      237458.167     1833544.701      237506.493
#Sta/Elev= 30
       0 1603.02     9.3 1603.14    18.6 1603.47    27.9 1603.58    37.2 1603.31
   39.421603.164    46.5  1602.7    74.4 1600.03    83.7 1599.23      93 1598.66
   120.9 1597.92   130.2 1597.47   167.9 1595.35   177.4 1594.42   186.9 1593.26
     206 1590.71   215.5 1589.32  222.15 1588.65     225  1588.4   234.5 1588.52
  236.17 1588.74   244.1 1589.96   253.6 1592.54   263.1 1595.36   291.7 1602.48
   310.8 1607.06   320.5 1609.52   349.8 1617.21   369.3 1621.83   408.4 1630.88
#Mann= 4 ,-1 , 0
       0     .06       0   39.42     .12       0  222.15    .045       0
  236.17     .12       0
#XS Ineff= 2 , 0
          196.08 1597.23
Permanent Ineff=
       F       F
Bank Sta=222.15,236.17
XS Rating Curve= 0 ,0
Exp/Cntr=0.3,0.1

Type RM Length L Ch R = 1 ,4431.2  ,140.4,139,139.5
XS GIS Cut Line= 2
     1833339.918      237169.799     1833403.461      237651.386
#Sta/Elev= 30
       0 1604.83     9.7 1604.68    29.2 1604.84    38.9 1604.45   44.321604.025
    77.7 1600.65    87.4 1599.78    97.2 1599.18   116.6 1598.34   184.6 1596.05
   213.7 1595.48   223.4 1594.73   233.2 1592.98   242.9  1590.4  248.75 1589.25
   252.6 1588.51   262.3 1588.96  263.79 1589.28   281.7 1594.08   291.5 1595.69
   320.6 1598.45     340 1599.87   349.8 1600.78   359.5 1601.87   369.2 1603.18
   388.6 1606.33   427.5 1613.49   446.9 1616.87   466.3 1619.79   485.8  1622.2
#Mann= 4 ,-1 , 0
       0     .06       0   44.32     .12       0  248.75    .045       0
  263.79     .12       0
Bank Sta=248.75,263.79
XS Rating Curve= 0 ,0
Exp/Cntr=0.3,0.1

Type RM Length L Ch R = 1 ,4292.2  ,59.9,54.1,47.6
XS GIS Cut Line= 2
     1833221.627      237206.112     1833285.751      237692.108
#Sta/Elev= 30
       0 1623.96   18.861622.669   39.821621.195      49 1619.93    68.6  1615.2
    78.4 1613.01    88.2 1611.08   117.6 1606.57   127.4  1604.7   166.7 1595.58
   176.5 1593.43   186.3 1591.77   196.1  1591.1   205.9 1591.42   225.5 1592.57
   235.3 1592.73   245.1  1592.6   274.5    1591   284.3 1589.81  293.15 1588.29
   303.9 1587.71  308.35 1588.27   313.7 1588.98   323.5 1590.75   333.3 1592.11
   362.8 1594.91   411.8 1600.66     451 1604.37   470.6 1606.44   490.2 1608.16
#Mann= 5 ,-1 , 0
       0     .06       0   18.86    .016       0   39.82     .12       0
  293.15    .045       0  308.35     .12       0
#XS Ineff= 2 , 0
          234.78 1594.46
Permanent Ineff=
       F       F
Bank Sta=293.15,308.35
XS Rating Curve= 0 ,0
Exp/Cntr=0.3,0.1

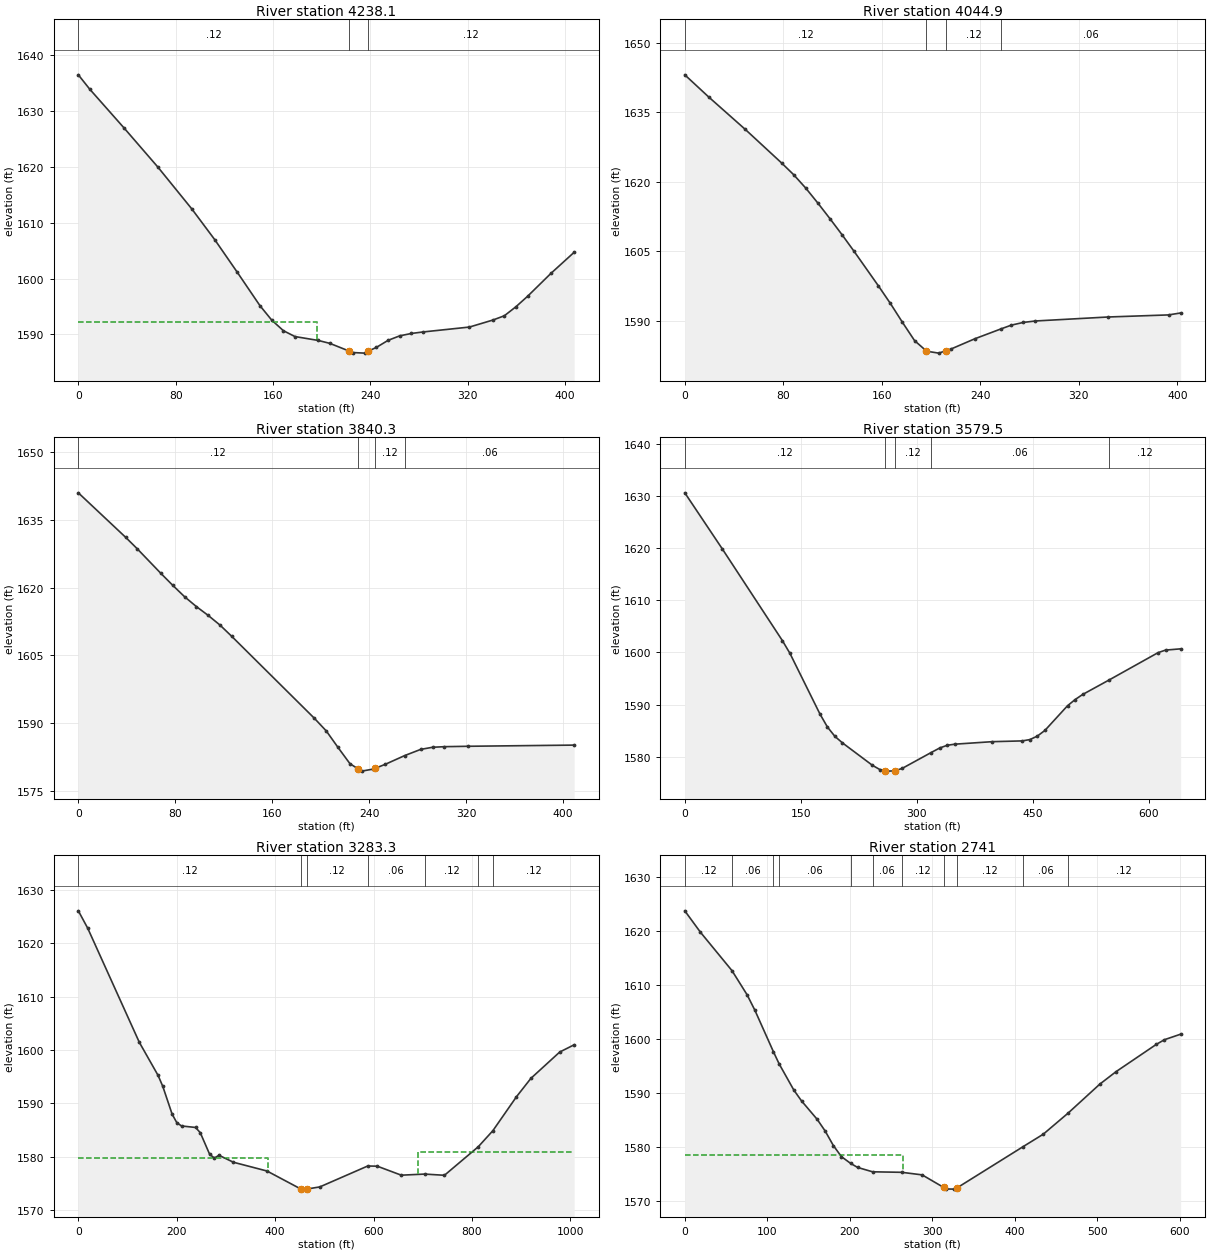
Type RM Length L Ch R = 1 ,4238.1  ,205.1,193.1,181.3
XS GIS Cut Line= 3
     1833074.127      237355.132     1833185.578      237454.694
     1833277.591      237696.014
#Sta/Elev= 29
       0 1636.48     9.3 1633.93    37.4 1627.01    65.4 1619.96    93.4 1612.44
   112.1 1606.98   130.8 1601.09   149.4 1595.12     159 1592.56   168.6 1590.66
   178.1 1589.61   197.3 1588.91   206.8 1588.39  222.54 1587.02     226 1586.74
   235.5 1586.64  238.26 1586.98   245.1 1587.67   254.7 1588.93   264.2 1589.73
   273.8 1590.16   283.4 1590.43   321.6 1591.31   340.8 1592.56   350.3 1593.33
   359.9 1594.96   369.4 1596.82   388.6 1600.92   407.7  1604.7
#Mann= 3 ,-1 , 0
       0     .12       0  222.54    .045       0  238.26     .12       0
#XS Ineff= 2 , 0
          196.08 1592.26
Permanent Ineff=
       F       F
Bank Sta=222.54,238.26
XS Rating Curve= 0 ,0
Exp/Cntr=0.3,0.1

Type RM Length L Ch R = 1 ,4044.9  ,203.5,204.7,205.9
XS GIS Cut Line= 2
     1832902.394      237513.656     1833215.091      237767.194
#Sta/Elev= 27
       0 1643.05    19.6 1638.22    49.1 1631.27    78.6 1624.02    88.4 1621.49
    98.2  1618.6     108 1615.38   117.8 1612.02   127.6 1608.56   137.5 1604.93
   157.1 1597.53   166.9 1593.71   176.7 1589.63   186.6 1585.66  195.85 1583.51
   196.4 1583.38   206.2 1582.97  212.42 1583.52     216 1583.84   235.6 1586.08
  256.461588.172   265.1 1589.01   274.9  1589.6   284.7 1589.91   343.7 1590.77
   392.8 1591.22   402.6 1591.64
#Mann= 4 ,-1 , 0
       0     .12       0  195.85    .045       0  212.42     .12       0
  256.46     .06       0
Bank Sta=195.85,212.42
XS Rating Curve= 0 ,0
Exp/Cntr=0.3,0.1

Type RM Length L Ch R = 1 ,3840.3  ,261.8,260.7,259.7
XS GIS Cut Line= 2
     1832770.647      237652.611     1833074.466      237926.917
#Sta/Elev= 25
       0 1640.93      39 1631.12    48.7 1628.55    68.2 1623.12      78 1620.48
    87.7 1617.98    97.5 1615.79   107.2 1613.85     117  1611.7   126.7 1609.21
   194.9 1591.11   204.7 1588.32   214.4 1584.67   224.2  1581.1  230.61    1580
   233.9 1579.45   243.6 1579.91   244.9 1580.05   253.4 1580.96  269.391582.882
   282.6 1584.25   292.4 1584.72   302.1 1584.85   321.6 1584.94   409.3  1585.2
#Mann= 4 ,-1 , 0
       0     .12       0  230.61    .045       0   244.9     .12       0
  269.39     .06       0
Bank Sta=230.61,244.9
XS Rating Curve= 0 ,0
Exp/Cntr=0.3,0.1

Type RM Length L Ch R = 1 ,3579.5  ,311.9,296.2,280.1
XS GIS Cut Line= 4
     1832662.819      237757.143     1832713.355      237954.694
     1832862.661      238077.958     1833102.244      238123.097
#Sta/Elev= 30
       0 1630.56    48.6  1619.8   126.2 1602.26   135.9 1599.84   174.8  1588.2
   184.5  1585.7   194.2 1583.91   203.9 1582.67   242.6 1578.38   252.3 1577.56
  258.68 1577.35     262 1577.26   271.8 1577.31   281.4  1577.8   318.41580.802
   329.8  1581.7   339.4 1582.21   349.1 1582.42   397.5  1582.9   436.5 1583.05
   446.3  1583.3     456 1583.97   465.8 1585.06     495 1589.78   504.8 1590.96
   514.6 1591.94  548.961594.731   612.1 1599.95   621.8 1600.44   641.3 1600.68
#Mann= 5 ,-1 , 0
       0     .12       0  258.68    .045       0   271.8     .12       0
   318.4     .06       0  548.96     .12       0
Bank Sta=258.68,271.8
XS Rating Curve= 0 ,0
Exp/Cntr=0.3,0.1

Type RM Length L Ch R = 1 ,3283.3  ,559.1,542.3,521.9
XS GIS Cut Line= 4
     1832326.203      238489.417     1832393.911      238211.639
     1832949.466      238211.639     1833098.772      238138.722
#Sta/Elev= 30
       0 1626.05    19.1 1622.79   123.9 1601.45     162 1595.26   171.6 1593.21
   190.6    1588   200.1 1586.41   209.7 1585.79   238.3 1585.51   247.8 1584.53
   266.8  1580.5   276.4 1579.79   285.9  1580.3   315.2    1579   383.4 1577.36
   451.6 1574.02   461.4 1573.97   464.4 1573.99   490.6 1574.38  588.16  1578.3
   607.6 1578.26   656.3 1576.58  703.911576.786     744 1576.56  812.761581.903
  842.381584.904   890.3 1591.25   919.7  1594.7   978.3 1599.63  1007.6 1600.98
#Mann= 7 ,-1 , 0
       0     .12       0   451.6    .045       0   464.4     .12       0
  588.16     .06       0  703.91     .12       0  812.76     .06       0
  842.38     .12       0
#XS Ineff= 2 , 0
          385.14 1579.83  691.02         1580.84
Permanent Ineff=
       F       F
Bank Sta=451.6,464.4
XS Rating Curve= 0 ,0
Exp/Cntr=0.3,0.1

Type RM Length L Ch R = 1 ,2741    ,216.2,204.4,192.9
XS GIS Cut Line= 3
     1832748.078      238614.417      1832791.48      238459.903
     1833105.716      238150.875
#Sta/Elev= 30
       0 1623.79    18.9 1619.84   57.211612.713    75.5 1608.25      85 1605.37
  107.551597.661  114.39 1595.44   132.2 1590.59   141.6 1588.57   160.5 1585.17
   170.3 1582.98   180.1 1580.32   189.9 1578.26  201.031577.012   209.5 1576.26
  227.691575.449  263.051575.355   287.8 1574.88  313.93 1572.55   317.2 1572.27
     327 1572.24   330.5 1572.51  410.461580.134   434.7 1582.42  464.511586.286
   503.3  1591.7   522.9    1594   571.8 1599.06   581.6 1599.92   601.2 1600.94
#Mann= 11 ,-1 , 0
       0     .12       0   57.21     .06       0  107.55     .12       0
  114.39     .06       0  201.03    .016       0  227.69     .06       0
  263.05     .12       0  313.93    .045       0   330.5     .12       0
  410.46     .06       0  464.51     .12       0
#XS Ineff= 2 , 0
           264.4 1578.51
Permanent Ineff=
       F       F
Bank Sta=313.93,330.5
XS Rating Curve= 0 ,0
Exp/Cntr=0.3,0.1

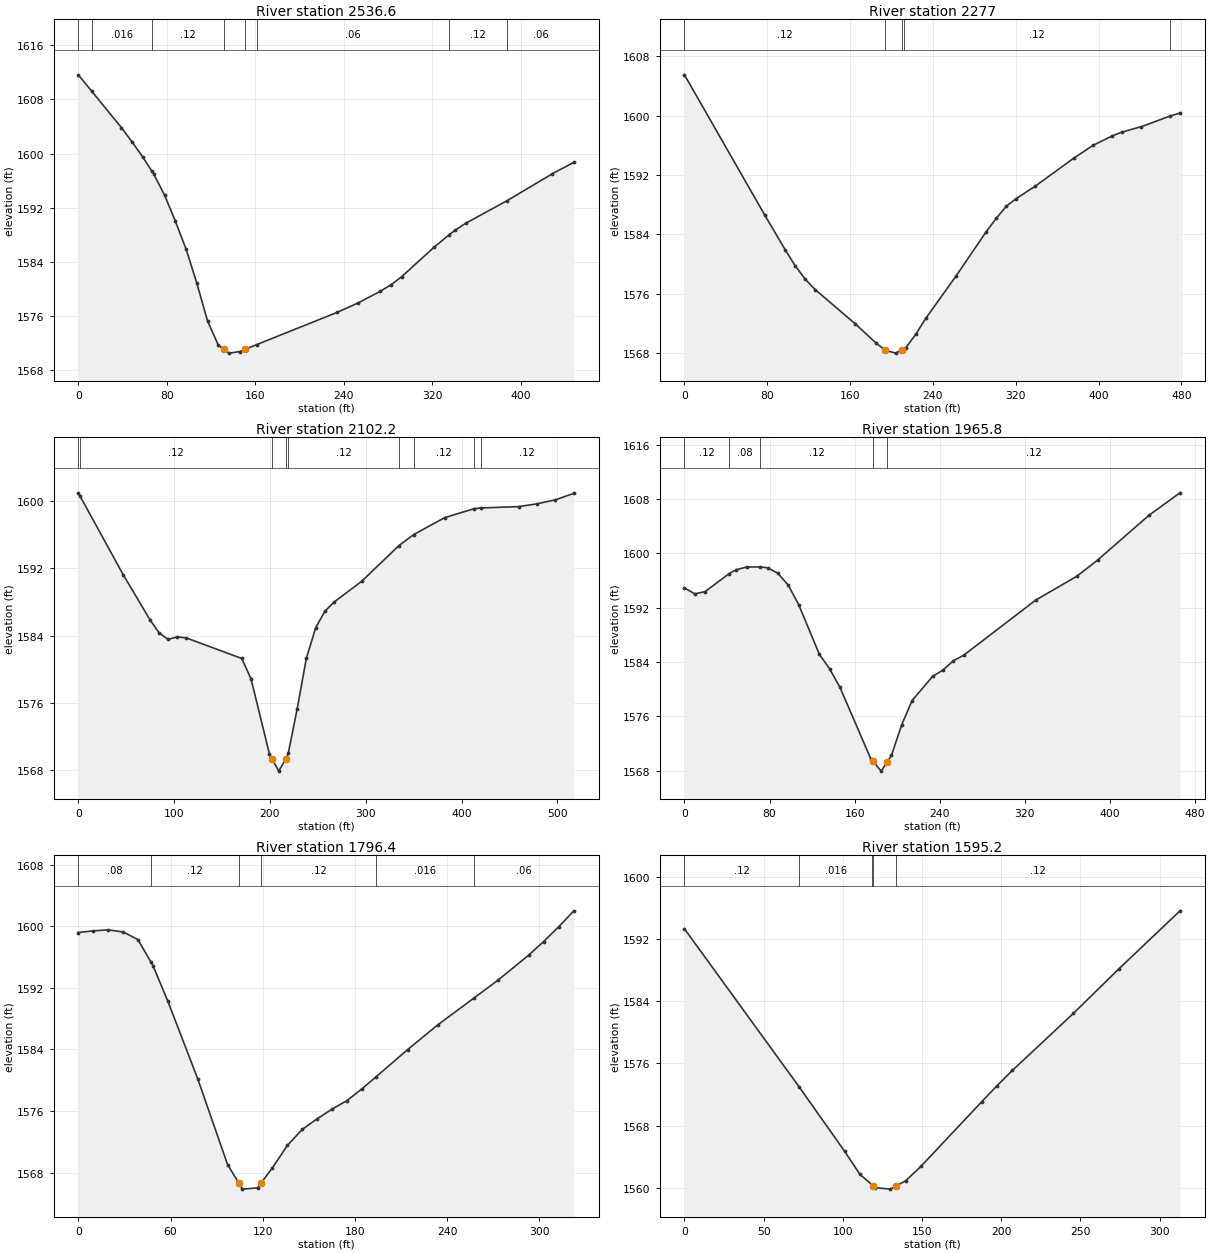
Type RM Length L Ch R = 1 ,2536.6  ,259.4,259.5,258.9
XS GIS Cut Line= 2
      1833010.23      238612.681     1833133.494      238182.125
#Sta/Elev= 30
       0 1611.62   12.211609.178    38.9 1603.84    48.7 1601.69    58.4 1599.45
   66.571597.374    68.2 1596.96    77.9 1593.88    87.6 1590.05    97.4 1585.88
   107.1 1580.86   116.8 1575.27   126.6 1571.69  131.61 1571.08   136.3 1570.53
     146 1570.76  150.49 1571.07  161.381571.801   233.7 1576.53   253.1 1577.96
   272.6 1579.64   282.3 1580.59   292.1  1581.8   321.3 1586.14  334.551587.932
   340.8 1588.71   350.5 1589.74  387.451593.037   428.4 1597.02   447.8  1598.7
#Mann= 8 ,-1 , 0
       0     .12       0   12.21    .016       0   66.57     .12       0
  131.61    .045       0  150.49     .12       0  161.38     .06       0
  334.55     .12       0  387.45     .06       0
Bank Sta=131.61,150.49
XS Rating Curve= 0 ,0
Exp/Cntr=0.3,0.1

Type RM Length L Ch R = 1 ,2277    ,193.8,174.8,156.6
XS GIS Cut Line= 3
     1833253.205      238676.579     1833334.883      238376.569
     1833258.494      238227.264
#Sta/Elev= 29
       0 1605.51    77.7 1586.58    97.2 1581.96   106.9 1579.79   116.6 1577.98
   126.3 1576.57   165.2 1571.93   184.6 1569.42  193.29 1568.48   194.3 1568.38
     204 1568.01  210.03 1568.46  212.061568.607   213.8 1568.74   223.5 1570.57
   233.2 1572.72   262.4 1578.42   291.5 1584.38   301.2 1586.18   310.9 1587.81
   320.2 1588.81   338.9 1590.52   376.2  1594.3   394.8 1596.02   413.4  1597.3
   422.7  1597.8   441.4 1598.53   468.81599.945   478.6 1600.36
#Mann= 5 ,-1 , 0
       0     .12       0  193.29    .045       0  210.03     .06       0
  212.06     .12       0   468.8     .06       0
Bank Sta=193.29,210.03
XS Rating Curve= 0 ,0
Exp/Cntr=0.3,0.1

Type RM Length L Ch R = 1 ,2102.2  ,141.5,136.4,135.9
XS GIS Cut Line= 3
     1833512.472      238740.995     1833511.832      238637.739
     1833318.959      238271.444
#Sta/Elev= 30
       0 1600.98     1.71600.613    46.9 1591.23    75.1 1585.82    84.5  1584.3
    93.9 1583.54   103.3 1583.85   112.9 1583.71   170.6 1581.27   180.3 1578.83
   199.5  1569.9   202.1 1569.35   209.2 1567.87  216.68 1569.36  219.151569.999
   228.4 1575.26     238 1581.28   247.7 1584.91   257.3 1586.88   266.9 1587.98
   295.8 1590.46  334.691594.706  350.081596.015   382.4 1598.03  413.371599.103
  420.15 1599.18   459.5 1599.34   478.7 1599.67     498 1600.15   517.2 1600.92
#Mann= 9 ,-1 , 0
       0     .06       0     1.7     .12       0   202.1    .045       0
  216.68     .06       0  219.15     .12       0  334.69     .06       0
  350.08     .12       0  413.37     .06       0  420.15     .12       0
Bank Sta=202.1,216.68
XS Rating Curve= 0 ,0
Exp/Cntr=0.3,0.1

Type RM Length L Ch R = 1 ,1965.8  ,138.2,169.4,194.2
XS GIS Cut Line= 3
      1833626.16      238736.975     1833625.374      238610.135
     1833467.426      238310.168
#Sta/Elev= 30
       0 1594.92     9.8 1594.03    19.5 1594.38   41.841597.003    48.8  1597.6
    58.5 1597.99   71.371598.017    78.1 1597.88    87.8 1597.08    97.6 1595.31
   107.3 1592.47   126.8 1585.14   136.5 1582.98   146.2 1580.25   175.3 1569.67
  177.16 1569.35     185 1567.91   190.6 1569.28   194.6 1570.26   204.3 1574.77
     214 1578.32   233.4 1581.89   243.1 1582.82   252.8 1584.18   262.4 1584.98
   330.2 1593.12     369 1596.65   388.4 1599.02   436.8 1605.64   465.8 1608.93
#Mann= 5 ,-1 , 0
       0     .12       0   41.84     .08       0   71.37     .12       0
  177.16    .045       0   190.6     .12       0
Bank Sta=177.16,190.6
XS Rating Curve= 0 ,0
Exp/Cntr=0.3,0.1

Type RM Length L Ch R = 1 ,1796.4  ,210.5,201.2,191.7
XS GIS Cut Line= 3
     1833678.633      238748.097     1833772.383      238600.528
     1833793.252      238454.446
#Sta/Elev= 30
       0  1599.2     9.7 1599.42    19.4 1599.54    29.1 1599.28    38.8 1598.28
   47.341595.326    48.6 1594.89    58.3 1590.24    77.7 1580.18    97.1 1569.04
   104.5  1566.6   106.8 1565.84   116.6    1566  118.68 1566.58   126.3 1568.62
     136 1571.52   145.7  1573.6   155.4 1574.99   165.1 1576.24   174.8 1577.35
   184.7 1578.91  193.831580.456   214.2 1583.97   233.9  1587.2  257.731590.727
   273.2 1593.03   292.9 1596.24   302.7 1598.02   312.6 1599.96   322.4 1602.02
#Mann= 6 ,-1 , 0
       0     .08       0   47.34     .12       0   104.5    .045       0
  118.68     .12       0  193.83    .016       0  257.73     .06       0
Bank Sta=104.5,118.68
XS Rating Curve= 0 ,0
Exp/Cntr=0.3,0.1

Type RM Length L Ch R = 1 ,1595.2  ,172.2,173.7,175.2
XS GIS Cut Line= 3
     1833892.175      238808.861     1833930.369      238715.111
     1833962.684      238505.915
#Sta/Elev= 17
       0 1593.34   72.361573.002   101.2 1564.67   110.8 1561.71  118.431560.372
   119.1 1560.26   120.5    1560   130.1 1559.81  133.56 1560.21   139.7 1560.89
   149.3 1562.74   187.8 1571.09   197.4 1573.14   207.1 1575.11   245.6 1582.45
   274.4  1588.2   312.9 1595.66
#Mann= 5 ,-1 , 0
       0     .12       0   72.36    .016       0  118.43     .12       0
   119.1    .045       0  133.56     .12       0
Bank Sta=119.1,133.56
XS Rating Curve= 0 ,0
Exp/Cntr=0.3,0.1