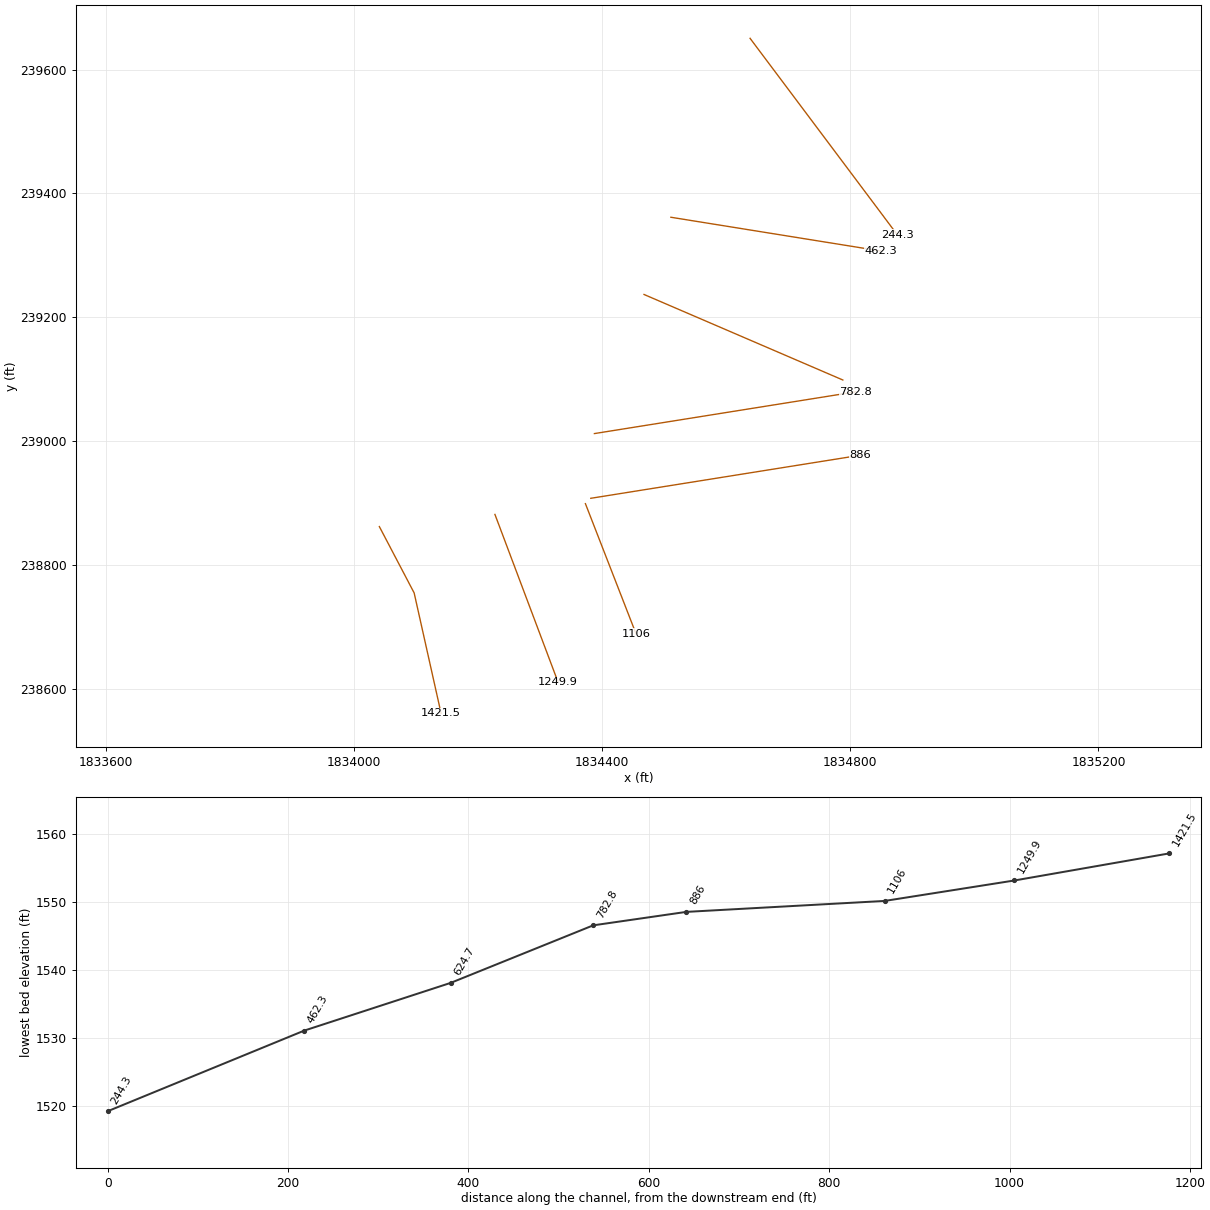
HEC-RAS study BONICARN.prj: BONICARN

--- BONICARN.g01 (geometry) --- (continued)

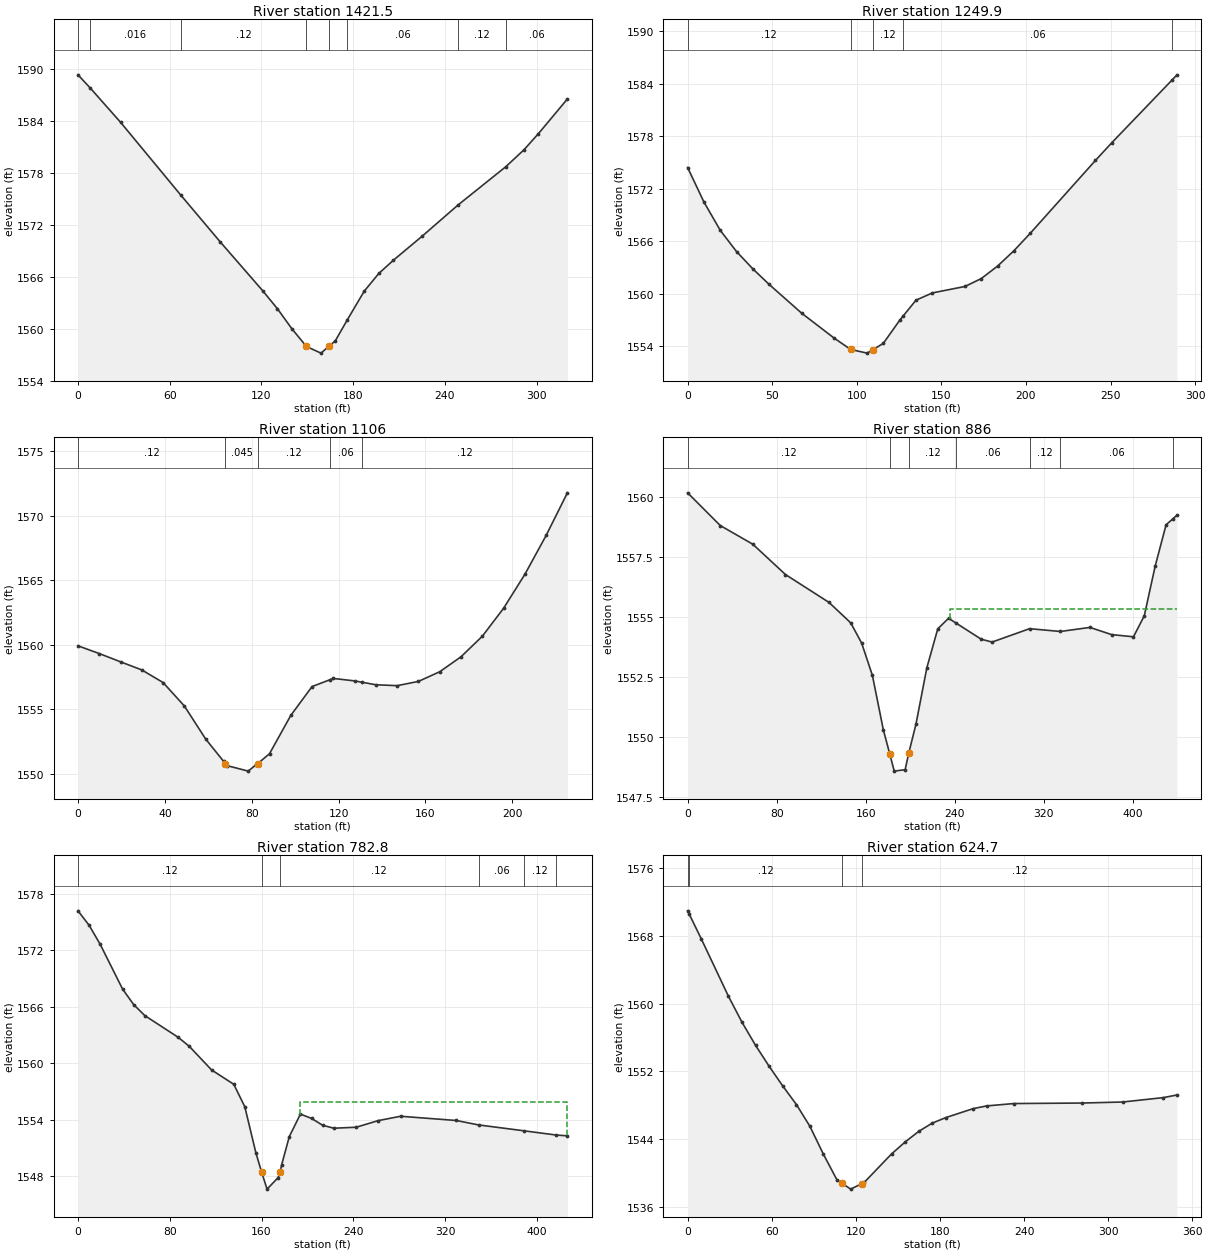
Type RM Length L Ch R = 1 ,1421.5  ,168.2,171.6,174.5
XS GIS Cut Line= 3
     1834040.933      238862.147     1834097.036      238755.042
     1834140.439      238560.597
#Sta/Elev= 22
       0 1589.29    8.021587.764    27.9  1583.8   67.161575.428      93 1570.02
   120.9 1564.36   130.4 1562.31   139.9 1559.99   149.4 1557.95   158.9 1557.18
  164.04 1557.96   168.3  1558.6  176.191561.033   187.3 1564.35   196.8 1566.38
   206.3  1567.9   225.3  1570.7  248.621574.277  279.76 1578.68   291.7 1580.64
   301.2 1582.51   320.1  1586.5
#Mann= 8 ,-1 , 0
       0     .12       0    8.02    .016       0   67.16     .12       0
   149.4    .045       0  164.04     .12       0  176.19     .06       0
  248.62     .12       0  279.76     .06       0
Bank Sta=149.4,164.04
XS Rating Curve= 0 ,0
Exp/Cntr=0.3,0.1

Type RM Length L Ch R = 1 ,1249.9  ,143.8,143.9,144.3
XS GIS Cut Line= 2
     1834227.244      238881.778     1834329.021      238610.948
#Sta/Elev= 25
       0 1574.41     9.6 1570.48    19.3 1567.23    28.9 1564.81    38.6 1562.82
    48.2 1561.05    67.5 1557.75    86.8 1554.89    96.4 1553.62   106.1  1553.2
  109.53 1553.59   115.7 1554.32   125.4 1556.96  127.231557.397     135 1559.25
   144.7 1560.08     164 1560.82   173.6 1561.72   183.2 1563.14   192.9  1564.9
   202.5 1566.88   241.1 1575.22   250.8 1577.25  286.361584.403   289.3    1585
#Mann= 5 ,-1 , 0
       0     .12       0    96.4    .045       0  109.53     .12       0
  127.23     .06       0  286.36     .12       0
Bank Sta=96.4,109.53
XS Rating Curve= 0 ,0
Exp/Cntr=0.3,0.1

Type RM Length L Ch R = 1 ,1106    ,188.3,219.9,250.5
XS GIS Cut Line= 2
     1834373.078      238899.139     1834454.675      238689.069
#Sta/Elev= 30
       0 1559.91     9.8 1559.31    19.6 1558.67    29.4 1558.04    39.2 1557.06
      49 1555.24    58.8 1552.68    67.1 1550.94   67.81 1550.76    68.6 1550.62
    78.4 1550.19    82.1  1550.7   82.83 1550.78    88.2 1551.54      98 1554.51
   107.8 1556.75  115.851557.267   117.6 1557.38   127.4 1557.19  130.961557.081
   137.2 1556.89     147 1556.82   156.8 1557.15   166.6  1557.9   176.4 1559.06
   186.2 1560.65     196 1562.82   205.8 1565.45   215.6 1568.47   225.4 1571.78
#Mann= 5 ,-1 , 0
       0     .12       0   67.81    .045       0   82.83     .12       0
  115.85     .06       0  130.96     .12       0
Bank Sta=67.81,82.83
XS Rating Curve= 0 ,0
Exp/Cntr=0.3,0.1

Type RM Length L Ch R = 1 ,886     ,102.9,103.3,102.8
XS GIS Cut Line= 2
     1834381.758      238907.819     1834815.786      238977.264
#Sta/Elev= 30
       0 1560.16    29.3  1558.8    58.6 1558.02    87.9 1556.76     127  1555.6
   146.5 1554.75   156.3 1553.91     166 1552.56   175.8  1550.3  181.54  1549.3
   185.6 1548.58   195.4 1548.64   198.7 1549.34   205.1 1550.53   214.9 1552.88
   224.7  1554.5   234.4 1554.94  241.48 1554.73   263.7 1554.07   273.5 1553.95
  307.161554.507   334.91554.391   361.4 1554.56   380.9 1554.26   400.5 1554.17
   410.2 1555.04     420 1557.11   429.8 1558.83  435.69 1559.07   439.6 1559.23
#Mann= 7 ,-1 , 0
       0     .12       0  181.54    .045       0   198.7     .12       0
  241.48     .06       0  307.16     .12       0   334.9     .06       0
  435.69     .12       0
#XS Ineff= 2 , 0
                          235.29         1555.31
Permanent Ineff=
       F       F
Bank Sta=181.54,198.7
XS Rating Curve= 0 ,0
Exp/Cntr=0.3,0.1

Type RM Length L Ch R = 1 ,782.8   ,170.5,158,144.7
XS GIS Cut Line= 2
     1834387.558      239012.289     1834808.841      239079.694
#Sta/Elev= 30
       0  1576.2     9.7 1574.66    19.4 1572.62    38.8 1567.89    48.5 1566.23
    58.2 1565.06    87.3 1562.75      97 1561.79   116.4 1559.28   135.8 1557.75
   145.4 1555.36   155.1 1550.44  160.07  1548.4   164.8  1546.6   174.5 1547.83
  176.21 1548.44   177.4 1549.13   184.2 1552.19   193.9 1554.58   203.6 1554.12
   213.3 1553.39     223 1553.08   242.4 1553.18   261.8 1553.89   281.2 1554.35
   329.7  1553.9  349.141553.429  389.051552.799  417.02 1552.35   426.6 1552.27
#Mann= 6 ,-1 , 0
       0     .12       0  160.07    .045       0  176.21     .12       0
  349.14     .06       0  389.05     .12       0  417.02     .06       0
#XS Ineff= 2 , 0
                           193.5         1555.82
Permanent Ineff=
       F       F
Bank Sta=160.07,176.21
XS Rating Curve= 0 ,0
Exp/Cntr=0.3,0.1

Type RM Length L Ch R = 1 ,624.7   ,156.8,162.4,168
XS GIS Cut Line= 2
      1834467.53       239236.87     1834788.008      239098.792
#Sta/Elev= 28
       0 1570.92    1.271570.489     9.7 1567.63    29.1 1560.86    38.8 1557.79
    48.5 1555.06    58.2 1552.59    67.8  1550.3    77.6  1548.1    87.2 1545.54
    96.9 1542.23   106.6  1539.2  110.09 1538.83   116.3 1538.14  124.28 1538.79
     126 1538.94   145.4 1542.28   155.1 1543.69   164.8 1544.94   174.5 1545.92
   184.2 1546.57   203.6 1547.62   213.2 1547.94   232.6 1548.22   281.1 1548.28
   310.2  1548.4   339.3 1548.92     349 1549.23
#Mann= 4 ,-1 , 0
       0    .016       0    1.27     .12       0  110.09    .045       0
  124.28     .12       0
Bank Sta=110.09,124.28
XS Rating Curve= 0 ,0
Exp/Cntr=0.3,0.1

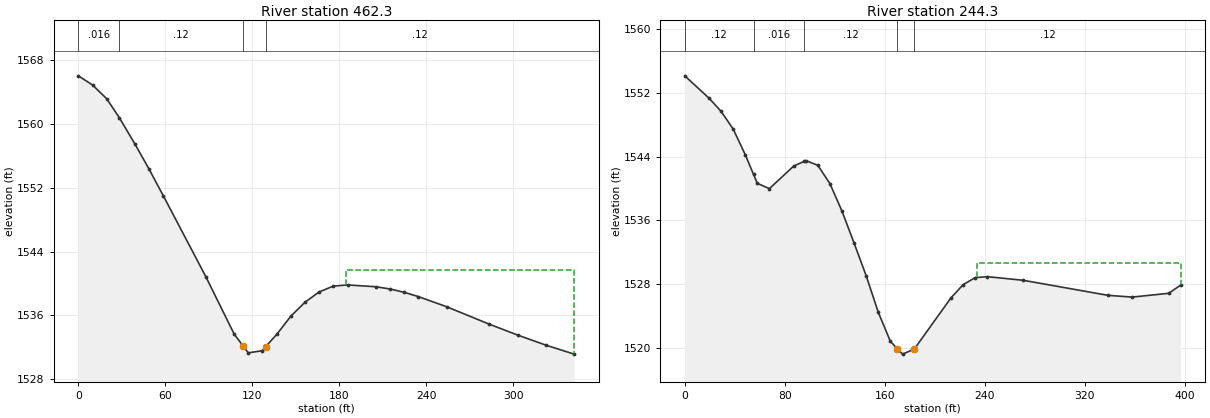
Type RM Length L Ch R = 1 ,462.3   ,235.3,218,200.3
XS GIS Cut Line= 2
     1834510.885      239361.517     1834848.772      239307.125
#Sta/Elev= 28
       0 1566.06     9.8 1564.91    19.6 1563.18   28.261560.814    39.1 1557.49
    48.9 1554.32    58.7 1550.98      88 1540.84   107.6 1533.62  113.91  1532.1
   117.3 1531.28   126.9 1531.55  129.36 1532.07   136.9 1533.59   146.7 1535.89
   156.4 1537.63   166.2 1538.93     176 1539.66   185.8 1539.81   205.3 1539.58
   215.1  1539.3   224.9 1538.88   234.7 1538.34   254.2 1537.07   283.6 1534.88
   303.1 1533.52   322.7 1532.25   342.2 1531.12
#Mann= 4 ,-1 , 0
       0    .016       0   28.26     .12       0  113.91    .045       0
  129.36     .12       0
#XS Ineff= 2 , 0
                          184.57         1541.62
Permanent Ineff=
       F       F
Bank Sta=113.91,129.36
XS Rating Curve= 0 ,0
Exp/Cntr=0.3,0.1

Type RM Length L Ch R = 1 ,244.3   ,249.4,244.3,238.7
XS GIS Cut Line= 2
     1834638.507      239650.353     1834876.172      239332.765
#Sta/Elev= 30
       0  1554.1    19.4  1551.3      29 1549.66    38.7 1547.44    48.4 1544.22
   55.031541.748      58 1540.64    67.7 1539.98    87.1  1542.8    95.21543.376
    96.8 1543.49   106.4  1542.9   116.1 1540.61   125.8 1537.15   135.4 1533.18
   145.1 1529.08   154.8  1524.5   164.5 1520.86  169.96 1519.95   174.2 1519.26
   183.6 1519.89   212.8 1526.27   222.5 1527.93   232.2 1528.83   241.9 1528.96
   270.9  1528.5   338.6 1526.62     358  1526.4     387 1526.87   396.7 1527.89
#Mann= 5 ,-1 , 0
       0     .12       0   55.03    .016       0    95.2     .12       0
  169.96    .045       0   183.6     .12       0
#XS Ineff= 2 , 0
                          234.06         1530.61
Permanent Ineff=
       F       F
Bank Sta=169.96,183.6
XS Rating Curve= 0 ,0
Exp/Cntr=0.3,0.1

Chan Stop Cuts=-1
Use User Specified Reach Order=0
Composite Channel Slope=5